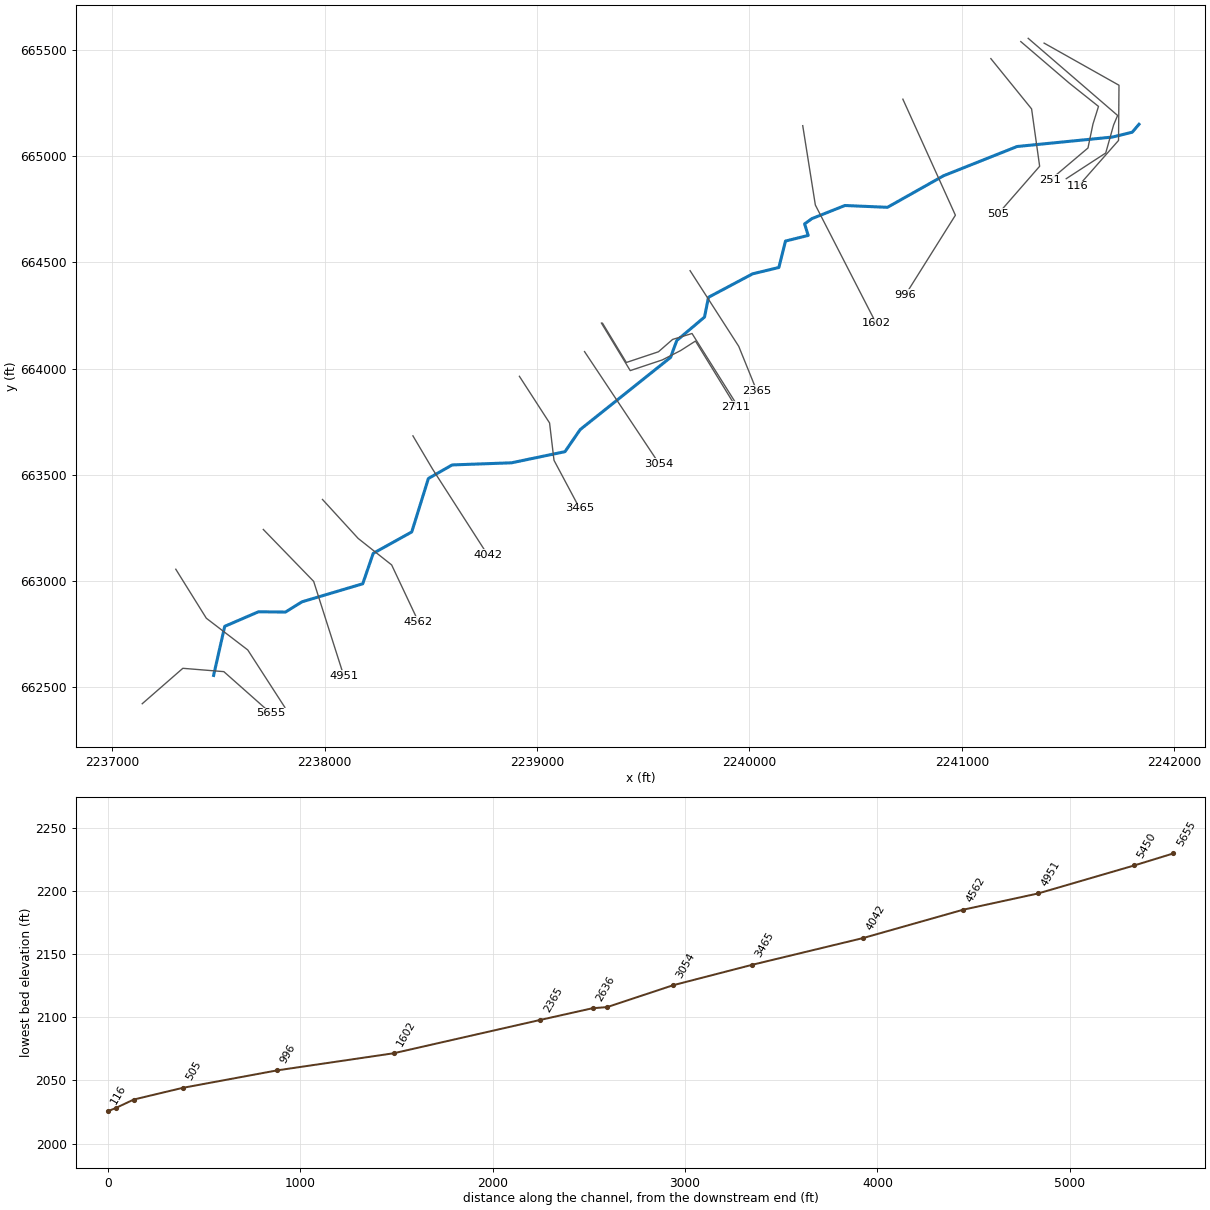
--- THREEFKRN.prj (project) ---

Proj Title=THREEFKRN
Current Plan=p01
Default Exp/Contr=0,0
English Units
Geom File=g01
Flow File=f01
Plan File=p01
BEGIN DESCRIPTION:
----------MODEL BY WSP USA 2022----------
AFH study
Randolph County, WV
HEC-RAS Version: RAS 6.2
Vertical Datum: NAVD88
Projection: NAD 1983 StatePlane West Virginia S FIPS 4702 (US Feet)
Terrain: 1-meter LIDAR (FEMA Region III 3DEP collected 2016-2018)
Land Use: 2019 NLCD
Hydrologic Method:
WV SIR2010-5033 regression equations
Additional Model Notes:
None
END DESCRIPTION:
DSS Export Rating Curves= 0
DSS Export Rating Curve Sorted= 0
DSS Export Volume Flow Curves= 0
DXF OffsetX= 0
DXF OffsetY= 0
DXF ScaleX= 0
DXF ScaleY= 0

--- THREEFKRN.p01 (plan) ---

Plan Title=Floodplain
Program Version=6.20
Short Identifier=Floodplain
Geom File=g01
Flow File=f01
Subcritical Flow
K Sum by GR= 0
Std Step Tol= 0.01
Critical Tol= 0.01
Num of Std Step Trials= 20
Max Error Tol= 0.3
Flow Tol Ratio= 0.001
Split Flow NTrial= 30
Split Flow Tol= 0.02
Split Flow Ratio= 0.02
Log Output Level= 0
Friction Slope Method= 1
Unsteady Friction Slope Method= 2
Unsteady Bridges Friction Slope Method= 1
Parabolic Critical Depth
Global Vel Dist= 0 , 0 , 0
Global Log Level= 0
CheckData=True
Encroach Param=-1 ,0,0, 0
Computation Interval=1MIN
Output Interval=1HOUR
Instantaneous Interval=1HOUR
Mapping Interval=1HOUR
Computation Time Step Use Courant=        0
Computation Time Step Use Time Series=    0
Computation Time Step Count To Double=0
Computation Time Step Max Doubling=0
Computation Time Step Max Halving=0
Computation Time Step Residence Courant=0
Run HTab= 0
Run UNet= 0
Run Sediment= 0
Run PostProcess= 0
Run WQNet= 0
Run RASMapper=-1
UNET Theta= 1
UNET Theta Warmup= 1
UNET ZTol= 0.02
UNET ZSATol= 0.02
UNET MxIter= 20
UNET Max Iter WO Improvement= 0
UNET MaxInSteps= 0
UNET DtIC= 0
UNET DtMin= 0
UNET MaxCRTS= 20
UNET WFStab= 2
UNET SFStab= 1
UNET WFX= 1
UNET SFX= 1
UNET Gravity=32.174
UNET 1D Methodology=Finite Difference
UNET DSS MLevel= 4
UNET Pardiso=0
UNET DZMax Abort= 100
UNET Use Existing IB Tables=-1
UNET Froude Reduction=False
UNET Froude Limit= 0.8
UNET Froude Power= 4
UNET D1 Cores= 0
UNET WindReference=Eulerian
UNET WindDragFormulation=Hsu (1988)
UNET D2 Coriolis=0
UNET D2 Cores= 0
UNET D2 Theta= 1
UNET D2 Theta Warmup= 1
UNET D2 Z Tol= 0.01
UNET D2 Volume Tol= 0.01
UNET D2 Max Iterations= 20
UNET D2 Equation= 0
UNET D2 RampUpFraction=0.1
UNET D2 TimeSlices= 1
UNET D2 Turbulence Formulation=None
UNET D2 Eddy Viscosity=0.3
UNET D2 Transverse Eddy Viscosity=0.1
UNET D2 Smagorinsky Mixing=0.05
UNET D2 BCVolumeCheck=0
UNET D2 Cores=0
UNET D2 SolverType=PARDISO (Direct)
UNET D2 Minimum Iterations= 2147483647
UNET D2 Maximum Iterations= 2147483647
UNET D2 Restart Number= 10
UNET D2 Relaxation Coeff=1.3
UNET D2 SOR Precondition Iterations= 10
UNET D2 ILUT Maximum Fill= 8
UNET D2 ILUT Tolerance=1E-08
UNET D1D2 MaxIter= 0
UNET D1D2 ZTol=0.01
UNET D1D2 QTol=0.1
UNET D1D2 MinQTol=1
Write IC File= 0
Write IC File at Fixed DateTime=0
Write IC File at Sim End=0
Echo Input=False
Echo Parameters=False
Echo Output=False
Write Detailed= 0
HDF Write Warmup=0
HDF Write Time Slices=0
HDF Flush=0
HDF Compression= 1
HDF Chunk Size= 1
HDF Spatial Parts= 1
HDF Use Max Rows=0
HDF Fixed Rows= 1
Calibration Method= 0
Calibration Iterations= 20
Calibration Max Change=0.05
Calibration Tolerance=0.2
Calibration Maximum=1.5
Calibration Minimum=0.5
Calibration Optimization Method= 1
WQ AD Non Conservative
WQ ULTIMATE=-1
WQ Max Comp Step=1HOUR
WQ Output Interval=15MIN
WQ Output Selected Increments= 0
WQ Output face flow=0
WQ Output face velocity=0
WQ Output face area=0
WQ Output face dispersion=0
WQ Output cell volume=0
WQ Output cell surface area=0
WQ Output cell continuity=0
WQ Output cumulative cell continuity=0
WQ Output face conc=0
WQ Output face dconc_dx=0
WQ Output face courant=0
WQ Output face peclet=0
WQ Output face adv mass=0
WQ Output face disp mass=0
WQ Output cell mass=0
WQ Output cell source sink temp=0
WQ Output nsm pathways=0
WQ Output nsm derived pathways=0
WQ Create Restart=0
WQ Fixed Restart=0
WQ System Summary=0
WQ Write To DSS=0
Sorting and Armoring Iterations= 10
XS Update Threshold= 0.02
Bed Roughness Predictor= 0
Hydraulics Update Threshold= 0.02
Energy Slope Method= 1
Volume Change Method= 1
Sediment Retention Method= 0
Sediment TS Multiplier= 1
Warm Up Method= 0
XS Weighting Method= 0
Number of US Weighted Cross Sections= 1
Number of DS Weighted Cross Sections= 1
Upstream XS Weight=0
Main XS Weight=1
Downstream XS Weight=0
Number of DS XS's Weighted with US Boundary= 1
Upstream Boundary Weight= 1
Weight of XSs Associated with US Boundary= 0
Number of US XS's Weighted with DS Boundary= 1
Downstream Boundary Weight= 0.5
Weight of XSs Associated with DS Boundary= 0.5
Percentile Method= 0
Sediment Output Level= 3
Mass or Volume Output= 0
Output Increment Type= 1
Profile and TS Output Increment= 1
Transport Output Increment 1
XS Output Flag= 0
XS Output Increment= 10
Read HDF5 Sediment Hotstart= 0
Sediment Hotstart Type= 0
Write Gradation File= 0
Read Gradation Hotstart= 0
Write HDF5 File= 1
Write Binary Output= 1
Write DSS Sediment File= 0
DSS Sediment Output Type= 1
SV Curve= 0
Specific Gage Flag= 0
Subcell Erosion Methods= 0
Subcell Deposition Methods= 0
Advection Scheme= 1
Matrix Solver= 0
Implicit Weighting Factor= 1
Maximum Outer Loop Convergence Iterations= 5
Convergence Maximum Absolute= 0.001
Convergence RMSE= 0.0001
Grain Fractions Max Abs Error= 0.001
Max Subgrid Regions= 1
Max Subgrid Length Scale= 3.402823E+38
Initial Layer Thickness= 3.402823E+38
Min Layer Thickness= 3.402823E+38
Max Layer Thickness= 3.402823E+38
Number of Layers= 5

--- THREEFKRN.f01 (steady flow) ---

Flow Title=Flow
Program Version=6.20
Number of Profiles= 1
Profile Names=P100yr
River Rch & RM=THREEFKRN,Main            ,5655
     528
Boundary for River Rch & Prof#=THREEFKRN,Main            , 1
Up Type= 0
Dn Type= 3
Dn Slope=0.06154
DSS Import GetInterval= 0
DSS Import GetPeak= 0
DSS Import FillOption= 0

--- THREEFKRN.g01 (geometry) ---

Geom Title=Geometry
Program Version=6.20

River Reach=THREEFKRN       ,Main
Reach XY= 30
2237477.25132429662555.5957034692237529.55700374662786.744369835
2237688.41134487662855.3206762522237815.58136611662854.018841609
2237893.27248368662902.1959105882238179.34141843662987.149490133
2238228.77574967663130.4943385122238410.19927134663231.188690916
2238488.49799928663482.9250641022238600.47710601663546.727101848
 2238879.9909827663556.7096934322239131.72735585663609.226976842
2239202.90765966663712.959709004 2239628.7251579664052.872463837
2239658.02945286 664132.54876484  2239788.584966664242.965538755
2239807.33492856664336.0211269412240014.97362088664446.437572777
2240138.58492219664476.2987335182240169.83485967 664600.69120127
2240276.67454106 664627.319756942240259.77037534664681.499766678
2240294.31394143664706.4203205262240449.52229244664768.139029101
2240649.94741653664759.5911459332240913.65555049664908.036715195
2241260.18044801 665045.925218942241709.88788193665090.483200684
2241802.20732128665113.2561277942241834.10154426665150.498500586

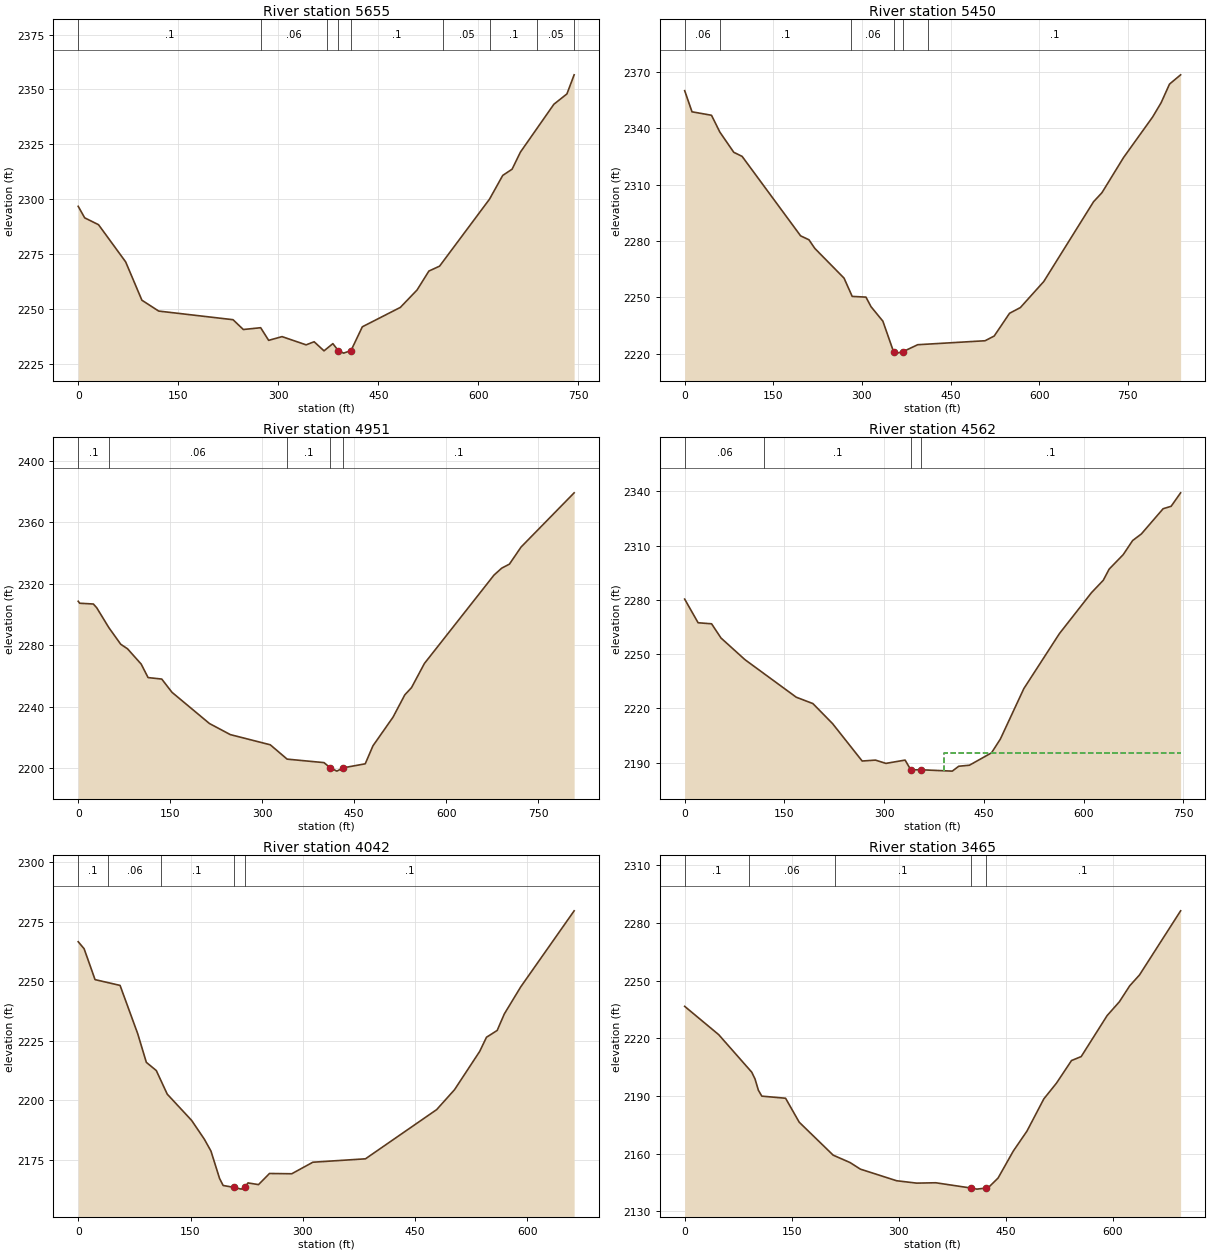
Type RM Length L Ch R = 1 ,5655    ,207.1,204.4,197.6
XS GIS Cut Line= 4
2237141.19496682662422.4039838542237332.44173438662589.199109904
2237525.43504777662573.4801975022237747.24636723662376.993792469
#Sta/Elev= 30
       0 2296.71     9.7 2291.47    30.5 2288.33    71.2 2271.38    95.5 2253.93
   120.7 2248.98   232.2 2245.05   247.6 2240.58   273.6  2241.4   285.6 2235.64
   305.7 2237.34   341.8 2233.59   353.8    2235   368.6 2230.86   381.9 2234.15
  389.86    2231     398 2229.82   409.12230.988   426.1 2241.82   483.1 2250.66
   508.2 2258.61   525.9 2267.22   541.9 2269.45   616.8 2299.98   636.6 2310.79
   650.7 2313.64   663.1 2321.39   713.3 2343.21   732.9 2347.94   743.7 2356.63
#Mann= 9 ,-1,0
       0      .1       0  273.76     .06       0  373.76      .1       0
  389.86    .045       0   409.1      .1       0   547.4     .05       0
   617.4      .1       0   687.4     .05       0  743.72      .1       0
Bank Sta=389.86,409.1
XS Rating Curve= 0 ,0
Exp/Cntr(USF)=0,0
Exp/Cntr=0.3,0.1

Type RM Length L Ch R = 1 ,5450    ,501.3,499.2,491.8
XS GIS Cut Line= 4
2237299.18231815663055.7017082082237443.01943102662824.884373477
2237638.03526183662675.6445038952237812.65768844662405.361085081
#Sta/Elev= 30
       0 2360.15    12.4 2348.89    45.4 2347.04    59.5 2338.09    83.1  2327.3
    97.2 2325.13   196.2 2282.77   210.3 2280.67   220.3 2276.05   269.7 2260.23
   283.5 2250.48   306.8 2250.11   315.4 2244.99   335.4  2237.3   353.52220.993
     359 2220.25   369.1 2220.97   394.3 2224.73   508.4 2226.85   523.8 2229.36
   549.8 2241.49   568.1 2244.53   607.7 2258.42   691.9 2300.93   706.2 2305.78
   742.6 2324.45   791.9 2346.11   806.2 2353.66   820.5 2363.65   839.3  2368.6
#Mann= 6 ,-1,0
       0     .06       0      60      .1       0  281.97     .06       0
   353.5    .045       0   369.1     .06       0  411.97      .1       0
Bank Sta=353.5,369.1
XS Rating Curve= 0 ,0
Exp/Cntr(USF)=0,0
Exp/Cntr=0.3,0.1

Type RM Length L Ch R = 1 ,4951    ,381,388.8,392.7
XS GIS Cut Line= 3
2237711.24789395663242.9231635712237948.38921989662998.412886159
     2238090.481662552.640715998
#Sta/Elev= 30
       0 2308.58     2.4 2307.29    24.7 2306.78    30.2 2304.34      50 2291.39
    69.3 2280.62    80.4 2277.66   102.7 2267.69   113.9 2258.93   136.2 2257.97
   152.9 2249.35     214 2229.04     248 2221.84   313.1 2215.22   340.6 2205.89
   400.7 2203.62   410.6 2200.34   421.7 2198.09   432.1 2200.24   467.9 2202.85
   480.5 2214.54   513.3 2233.24   532.4 2247.68   543.4 2252.42   564.4 2268.11
   677.8 2325.58   690.4  2330.1     703 2332.73   721.9  2343.8   808.5  2379.1
#Mann= 5 ,-1,0
       0      .1       0      50     .06       0     340      .1       0
   410.6    .045       0   432.1      .1       0
Bank Sta=410.6,432.1
XS Rating Curve= 0 ,0
Exp/Cntr(USF)=0,0
Exp/Cntr=0.3,0.1

Type RM Length L Ch R = 1 ,4562    ,521.6,520.4,517.3
XS GIS Cut Line= 4
2237989.93230497663384.0946530862238157.94667608663200.556598761
2238315.54569503663075.8918585982238441.89775255662807.837524865
#Sta/Elev= 30
       0 2280.41    20.2 2267.32    40.5 2266.74    54.6  2258.9    90.7  2246.9
   167.9 2226.12   192.9 2222.61   222.5 2211.52     267 2190.83     287 2191.33
   302.7 2189.52   331.6 2191.35  340.222185.928   355.3 2185.99   402.6 2185.24
   412.3 2187.94   428.4 2188.51   461.6 2195.35   474.9 2202.97   510.3 2230.93
   563.8 2261.34     612 2283.96   629.7  2290.8   638.6    2297   659.7 2304.99
   673.9  2312.8   687.1 2316.47   719.8 2330.41   731.8 2331.75   746.1  2339.2
#Mann= 4 ,-1,0
       0     .06       0     120      .1       0  340.22    .045       0
   355.3      .1       0
#XS Ineff= 2 , 0
                          389.54         2195.06
Permanent Ineff=
       F       F
Bank Sta=340.22,355.3
XS Rating Curve= 0 ,0
Exp/Cntr(USF)=0,0
Exp/Cntr=0.3,0.1

Type RM Length L Ch R = 1 ,4042    ,580.6,577.4,573.4
XS GIS Cut Line= 3
2238415.72702097663683.5495967652238507.84658898663527.736829838
2238767.98355362663122.655815458
#Sta/Elev= 30
       0 2266.52     7.9 2263.58    22.5 2250.63    55.9 2248.21    79.5 2227.93
      91 2215.95   104.3 2212.51   118.9 2202.62   151.5  2191.6   168.5 2183.71
   177.3 2178.75   188.8 2167.26   193.6 2164.32   207.8 2163.53   217.8 2162.79
  222.72 2163.61   226.8  2165.4   240.8 2164.68   255.5 2169.35   285.2 2169.23
   313.4 2174.07   383.7  2175.5   478.8 2196.14   502.6 2204.47   536.3 2220.57
   545.3 2226.47   559.6 2229.33   569.1 2236.23   591.3 2247.71   662.4 2279.48
#Mann= 5 ,-1,0
       0      .1       0      40     .06       0     110      .1       0
   207.8    .045       0  222.72      .1       0
Bank Sta=207.8,222.72
XS Rating Curve= 0 ,0
Exp/Cntr(USF)=0,0
Exp/Cntr=0.3,0.1

Type RM Length L Ch R = 1 ,3465    ,408,410.2,417
XS GIS Cut Line= 4
2238917.01468065 663963.942979032239059.02421989663744.346127022
2239079.87698405663568.5620439382239200.53780108663342.285502696
#Sta/Elev= 30
       0 2236.64    47.7 2221.91      94 2202.39    98.6 2198.84   103.3    2193
   108.1 2189.93   141.4 2188.84   160.5 2176.38   208.1 2159.23   231.9 2155.36
   246.2 2151.96   296.9 2145.93   325.1 2144.68   351.8 2144.87   401.7  2142.1
   409.7 2141.56   421.8 2142.12   427.4 2143.03   439.2 2147.33   460.5 2161.35
   479.7 2171.76   503.3  2188.5   521.1 2196.73   542.1 2208.45   555.7 2210.52
     592 2231.83   609.2 2239.03   623.7 2247.34   637.3 2252.93     695 2286.33
#Mann= 5 ,-1,0
       0      .1       0      90     .06       0     210      .1       0
   401.7    .045       0   421.8      .1       0
Bank Sta=401.7,421.8
XS Rating Curve= 0 ,0
Exp/Cntr(USF)=0,0
Exp/Cntr=0.3,0.1

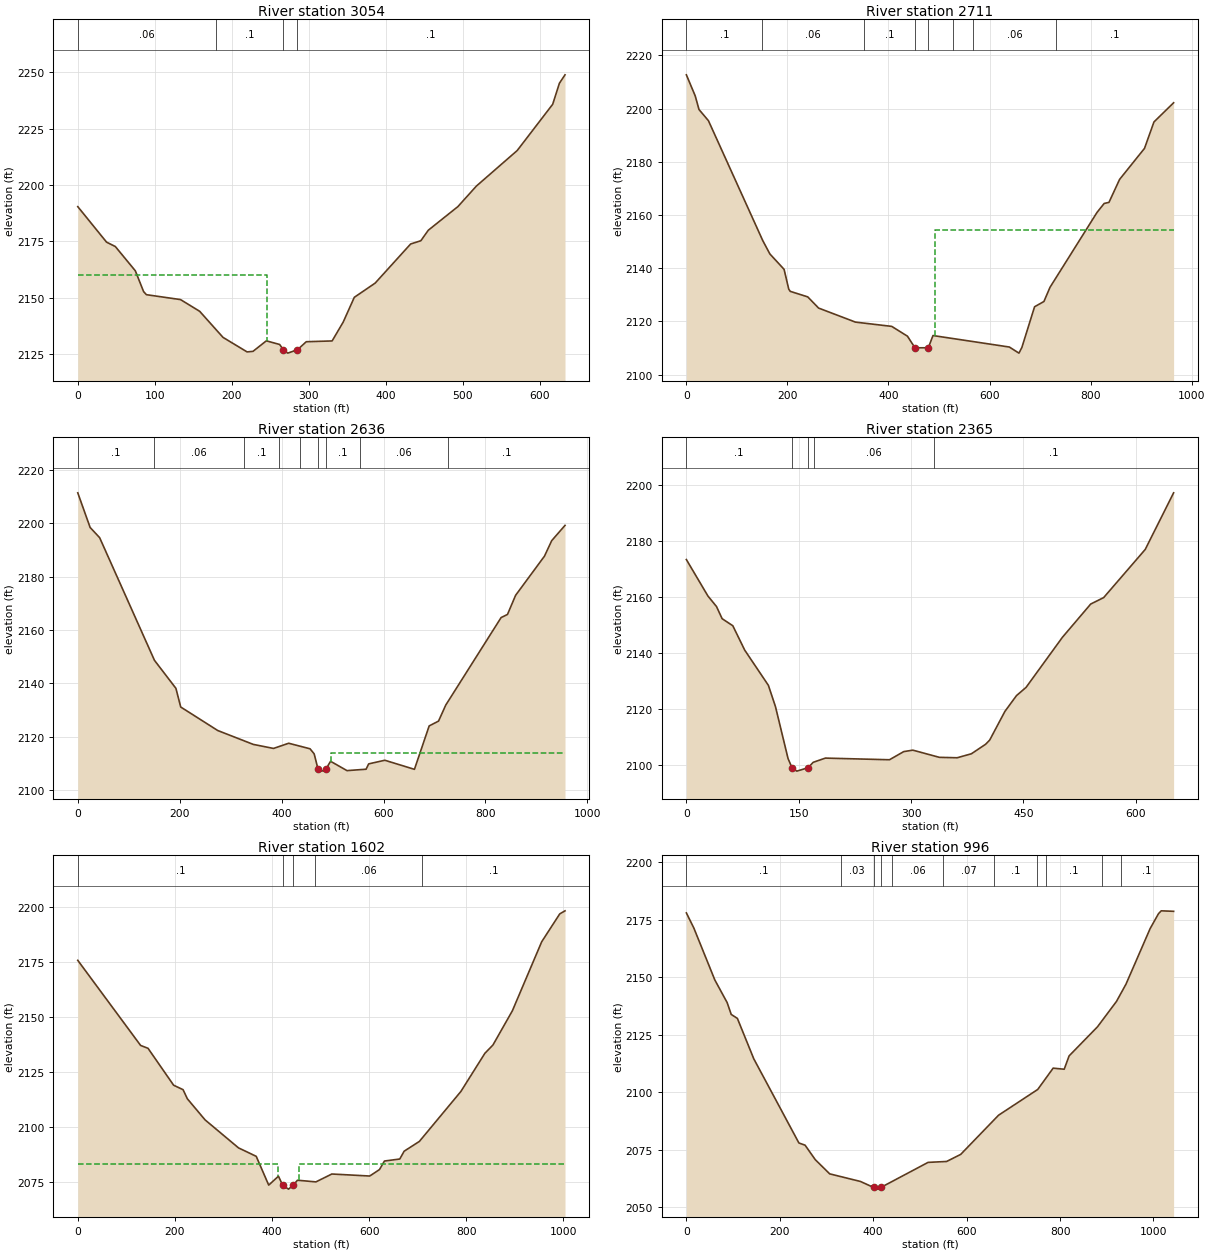
Type RM Length L Ch R = 1 ,3054    ,323.4,343,354.2
BEGIN DESCRIPTION:
Structure XS 4
END DESCRIPTION:
XS GIS Cut Line= 2
2239223.62911107664080.319616136  2239574.384301663553.228483722
#Sta/Elev= 30
       0 2190.41    37.4 2174.66    48.8 2172.71    74.8 2161.94    85.5 2152.73
    89.2 2151.34   133.5 2149.17   158.4 2143.97   188.7  2132.4     220 2125.95
   227.7  2126.2     245 2130.87   262.3 2129.25  267.252126.842   272.8 2125.41
   285.4 2126.89   296.9 2130.47   330.5 2130.82   344.9 2139.19   359.3 2150.17
   386.4 2156.48   432.5 2173.84   445.8 2175.29   455.4 2179.93   493.9 2190.43
   517.9 2199.53     571 2215.32   617.1 2235.85   625.8 2245.16   633.1 2248.91
#Mann= 4 ,-1,0
       0     .06       0     180      .1       0  267.25    .045       0
   285.4      .1       0
#XS Ineff= 2 , 0
          245.74 2159.96
Permanent Ineff=
       F       F
Bank Sta=267.25,285.4
XS Rating Curve= 0 ,0
Exp/Cntr(USF)=0,0
Exp/Cntr=0.3,0.1

Type RM Length L Ch R = 1 ,2711    ,85.3,75.6,68.2
BEGIN DESCRIPTION:
Structure XS 3
END DESCRIPTION:
XS GIS Cut Line= 6
 2239303.1267309664214.5685937552239438.78125541663990.808553336
2239589.81928269 664041.154562432239675.92163619664085.075598044
2239745.98809276664129.9602044782239936.05301636663820.056376667
#Sta/Elev= 30
       0 2212.69    17.5 2204.77      25 2199.65    43.7 2195.44   151.3 2150.34
   165.3 2145.36   193.4 2139.57   202.6 2132.12   205.6 2131.31   240.2 2129.23
   261.7 2125.02   334.6 2119.75   406.4 2118.14   437.5 2114.46   452.4  2110.1
  478.78  2110.1   488.1  2114.7   639.2 2110.38   658.2 2108.09     664 2110.23
   689.1 2125.51   707.6 2127.49   719.7 2132.84   812.8    2161   826.9 2164.35
   836.3 2164.74   857.4 2173.39   906.7 2185.05   925.4 2194.98   964.3 2202.19
#Mann= 8 ,-1,0
       0      .1       0     150     .06       0  351.67      .1       0
   452.4    .045       0  478.78     .06       0  527.55      .1       0
  567.55     .06       0  730.76      .1       0
#XS Ineff= 2 , 0
                          492.13         2154.41
Permanent Ineff=
       F       F
Bank Sta=452.4,478.78
XS Rating Curve= 0 ,0
Exp/Cntr(USF)=0,0
Exp/Cntr=0.3,0.1

Type RM Length L Ch R = 1 ,2636    ,277.4,270.9,265.2
BEGIN DESCRIPTION:
Structure XS 2
END DESCRIPTION:
XS GIS Cut Line= 6
2239308.35757398664213.8650105122239420.52096985664029.065866374
2239571.55899713664079.4118754682239638.24267185664137.575647336
2239729.75775011 664165.510926972239937.74003064663835.041839893
#Sta/Elev= 30
       0 2211.32    24.2 2198.37    42.9 2194.55   150.5 2148.66   192.6 2138.18
     202  2131.2   274.7  2122.4   344.4 2117.21   384.2  2115.7   413.9 2117.64
   455.8 2115.57   463.9 2113.68  471.46    2108   479.2 2107.21   487.1    2108
   496.1 2110.89   528.3  2107.4   565.8 2107.92   570.9 2109.92   602.6 2111.28
   660.7 2107.88   689.6 2124.12     708 2125.92   722.1  2131.9   830.8 2164.66
   843.3 2165.82   859.2 2172.97   915.9 2187.63   930.1 2193.43   956.2 2199.14
#Mann= 9 ,-1,0
       0      .1       0     150     .06       0  326.13      .1       0
  395.39     .06       0  435.39      .1       0  471.46    .045       0
   487.1      .1       0  552.92     .06       0  725.78      .1       0
#XS Ineff= 2 , 0
                          497.02         2114.08
Permanent Ineff=
       F       F
Bank Sta=471.46,487.1
XS Rating Curve= 0 ,0
Exp/Cntr(USF)=0,0
Exp/Cntr=0.3,0.1

Type RM Length L Ch R = 1 ,2365    ,757.8,762.9,753.9
BEGIN DESCRIPTION:
Structure XS 1
END DESCRIPTION:
XS GIS Cut Line= 3
2239720.62324297664461.2907214132239949.61480636664105.189434268
2240035.00149102663894.633632331
#Sta/Elev= 30
       0 2173.29    28.7 2160.35    40.3 2156.54    47.7 2152.25      62 2149.73
    77.9 2141.05   109.5 2128.51     119 2120.89   135.8  2102.4  141.08 2099.15
   147.4 2097.96   162.52099.162   169.3 2101.09   185.6  2102.6   271.2 2102.01
   290.2 2104.91   302.4 2105.43   337.8 2102.87   361.6 2102.72   380.6 2104.14
   399.6 2107.53     405 2109.01   425.3 2119.22   440.8 2124.86   453.6 2127.79
   502.1 2145.61   539.9 2157.46   557.2 2159.75   612.7  2176.9   650.6 2197.06
#Mann= 5 ,-1,0
       0      .1       0  141.08    .045       0   162.5      .1       0
     170     .06       0     330      .1       0
Bank Sta=141.08,162.5
XS Rating Curve= 0 ,0
Exp/Cntr(USF)=0,0
Exp/Cntr=0.3,0.1

Type RM Length L Ch R = 1 ,1602    ,605.4,605.4,602.9
XS GIS Cut Line= 3
2240250.97764552665144.0853560982240310.39519135664770.329825841
2240595.98275037664214.488268023
#Sta/Elev= 30
       0 2175.63   129.4 2136.91   144.7  2135.6   197.4 2118.81   216.8 2116.79
   225.7 2112.63   262.1 2103.05     331  2090.3   367.5 2086.45   393.2 2073.36
   413.3 2077.41   422.2 2073.19   434.1 2071.53   443.6  2073.3   452.4 2075.58
   490.5 2074.82   523.2 2078.41   601.2 2077.49   621.3 2080.42   631.6 2084.32
   663.1 2085.23   672.1 2088.78   703.5 2093.24     789 2115.98   838.4 2133.34
     855 2137.11     895 2152.68   955.4 2184.09   992.6 2196.78  1003.4 2198.16
#Mann= 5 ,-1,0
       0      .1       0   422.2    .045       0   443.6      .1       0
  488.45     .06       0  708.45      .1       0
#XS Ineff= 2 , 0
          412.71 2083.07  455.18         2082.97
Permanent Ineff=
       F       F
Bank Sta=422.2,443.6
XS Rating Curve= 0 ,0
Exp/Cntr(USF)=0,0
Exp/Cntr=0.3,0.1

Type RM Length L Ch R = 1 ,996     ,493.2,491.2,488
XS GIS Cut Line= 3
2240722.48462215665268.6705328512240969.73828063664722.412450167
2240733.98479231664346.740224883
#Sta/Elev= 30
       0 2178.05      16 2171.47    60.9 2148.92    87.3 2139.06      96 2133.92
   109.2  2132.2   144.3 2114.63   240.9 2078.04   254.1 2077.09   275.9  2070.8
   306.8 2064.62   372.7 2061.31  401.08 2058.69   407.8 2057.98   416.6 2058.74
   517.5 2069.61   557.1    2070   587.3 2073.08   668.4 2090.12   752.2 2101.31
   785.2 2110.57   808.9  2110.1   819.3 2115.88   880.2 2128.56   920.8 2139.58
   941.2 2147.11     993 2171.31  1010.8 2177.74  1016.6 2178.96  1043.1 2178.75
#Mann= 11 ,-1,0
       0      .1       0     330     .03       0  401.08    .045       0
   416.6     .03       0     440     .06       0     550     .07       0
  659.61      .1       0  749.61     .06       0  769.61      .1       0
  889.61     .06       0  929.61      .1       0
Bank Sta=401.08,416.6
XS Rating Curve= 0 ,0
Exp/Cntr(USF)=0,0
Exp/Cntr=0.3,0.1

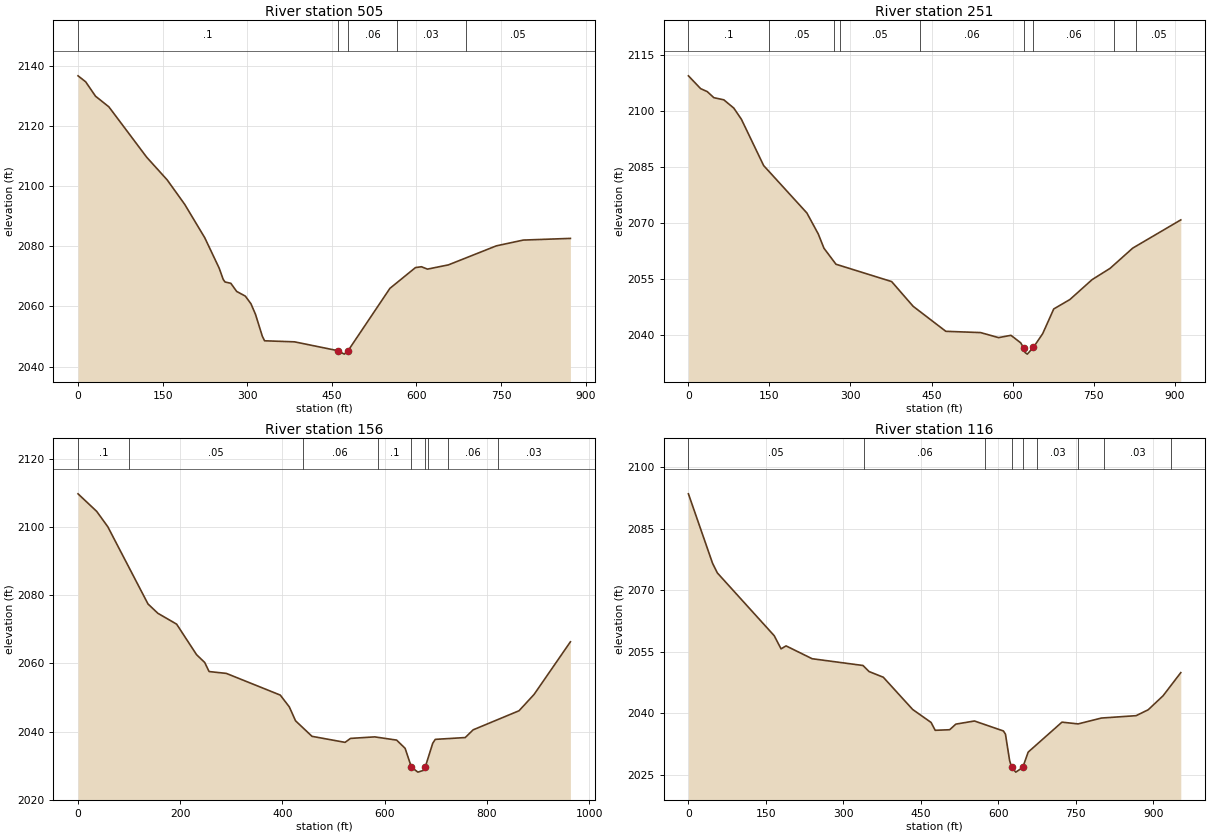
Type RM Length L Ch R = 1 ,505     ,257.4,254,251.1
BEGIN DESCRIPTION:
Structure XS 4
END DESCRIPTION:
XS GIS Cut Line= 4
2241136.67124688665459.6814708362241328.50941596665222.844225053
2241366.40337529664952.8497648622241172.19683374664730.222753826
#Sta/Elev= 30
       0 2136.78    13.5  2134.8      31    2130    54.7 2126.45   121.6 2109.71
   158.1 2102.12   189.1    2094   224.6  2082.9   250.3 2072.72   257.4 2068.99
   260.6 2068.15   270.9 2067.71   281.2 2065.01   296.6 2063.44   306.5 2060.92
   314.5 2057.44   326.7 2050.11   330.7 2048.57   383.9 2048.22     460  2045.3
   472.1 2044.13  478.952045.324   552.9 2066.02   598.2 2072.94   608.8 2073.22
   619.5 2072.43   656.6 2073.84   741.5 2080.17   789.3  2082.1   872.9 2082.66
#Mann= 5 ,-1,0
       0      .1       0     460    .045       0  478.95     .06       0
  564.78     .03       0  687.43     .05       0
Bank Sta=460,478.95
XS Rating Curve= 0 ,0
Exp/Cntr(USF)=0,0
Exp/Cntr=0.3,0.1

Type RM Length L Ch R = 1 ,251     ,96.3,94.9,92.5
BEGIN DESCRIPTION:
Structure XS 3
END DESCRIPTION:
XS GIS Cut Line= 6
2241277.68570873665539.8558498212241504.99240035665345.021771505
2241643.50295285665234.6860873432241617.45085581665151.793051319
2241593.98087255665038.9096895152241416.19945995664888.508938236
#Sta/Elev= 30
       0 2109.42    22.6 2105.99    34.9 2105.19    47.1 2103.57    65.6 2102.99
      84 2100.78    98.1 2097.78   139.3 2085.38   219.3 2072.69   240.4 2067.07
   250.9 2063.25   273.2 2058.96   376.2 2054.32     416  2047.7   476.5    2041
   540.9 2040.66   574.2 2039.31   597.1 2039.93   615.1 2037.92  620.392036.606
   623.2 2035.33   627.3 2034.89  638.782036.726   655.9 2040.39   676.3 2046.99
   706.1  2049.5   747.3 2054.84   780.6 2057.86   822.5 2063.28   911.5 2070.84
#Mann= 9 ,-1,0
       0      .1       0     150     .05       0     270      .1       0
     280     .05       0  429.38     .06       0  620.39    .045       0
  638.78     .06       0  788.65     .03       0  828.65     .05       0
Bank Sta=620.39,638.78
XS Rating Curve= 0 ,0
Exp/Cntr(USF)=0,0
Exp/Cntr=0.3,0.1

Type RM Length L Ch R = 1 ,156     ,38.4,40.3,46.9
BEGIN DESCRIPTION:
Structure XS 2
END DESCRIPTION:
XS GIS Cut Line= 5
 2241312.5332929665555.1962315312241733.50110625665192.055383102
2241714.55412659665147.0563064032241677.45154486 665015.19672468
2241491.59135094664894.400109296
#Sta/Elev= 30
       0 2109.79    36.5 2104.64    58.2 2100.14   136.9 2077.45   156.2 2074.72
   192.9 2071.53     232 2062.55   247.9 2060.27   256.4 2057.61   290.1 2057.07
   395.7  2050.7   413.4 2047.24   425.6 2043.15   457.8 2038.59   522.5 2036.82
   533.1 2037.98   580.5 2038.43   623.4 2037.48     640 2035.07652.28442029.542
   664.9 2028.08   677.4 2028.66  679.35 2029.56     694 2036.55     699  2037.7
   757.6 2038.23   773.1  2040.5   862.9  2046.1   892.3 2050.89   963.4 2066.34
#Mann= 9 ,-1,0
       0      .1       0     100     .05       0     440     .06       0
  585.95      .1       0652.2844    .045       0  679.35      .1       0
  684.78     .03       0  724.78     .06       0  821.76     .03       0
Bank Sta=652.2844,679.35
XS Rating Curve= 0 ,0
Exp/Cntr(USF)=0,0
Exp/Cntr=0.3,0.1

Type RM Length L Ch R = 1 ,116     ,,,
XS GIS Cut Line= 4
2241387.43868915665532.6917831992241739.98219777665334.318677433
2241737.82596836665074.4930334682241546.99966553664857.791977713
#Sta/Elev= 30
       0  2093.5    46.7 2076.57      56 2074.21   166.1 2058.89   179.3 2055.69
     189 2056.41   239.5 2053.28   337.9 2051.63   349.7 2050.15   377.2 2048.77
   434.1  2040.9   469.7 2037.74   477.7 2035.82   505.7 2035.96   517.7 2037.33
   553.7 2038.09   609.7 2035.66   613.7 2034.88   621.7 2028.48   625.7 2026.77
   633.7 2025.62  647.13 2026.76   657.7 2030.51   723.1 2037.81   754.3 2037.38
   799.4 2038.81   866.6 2039.39     890 2040.83   918.7 2044.23   953.1 2049.89
#Mann= 9 ,-1,0
       0     .05       0     340     .06       0  574.52      .1       0
   625.7    .045       0  647.13      .1       0  674.36     .03       0
  754.36     .06       0  804.36     .03       0  934.36     .05       0
Bank Sta=625.7,647.13
XS Rating Curve= 0 ,0
Exp/Cntr(USF)=0,0
Exp/Cntr=0.3,0.1
LCMann Table=0

Chan Stop Cuts=-1
Use User Specified Reach Order=0
Composite Channel Slope=5